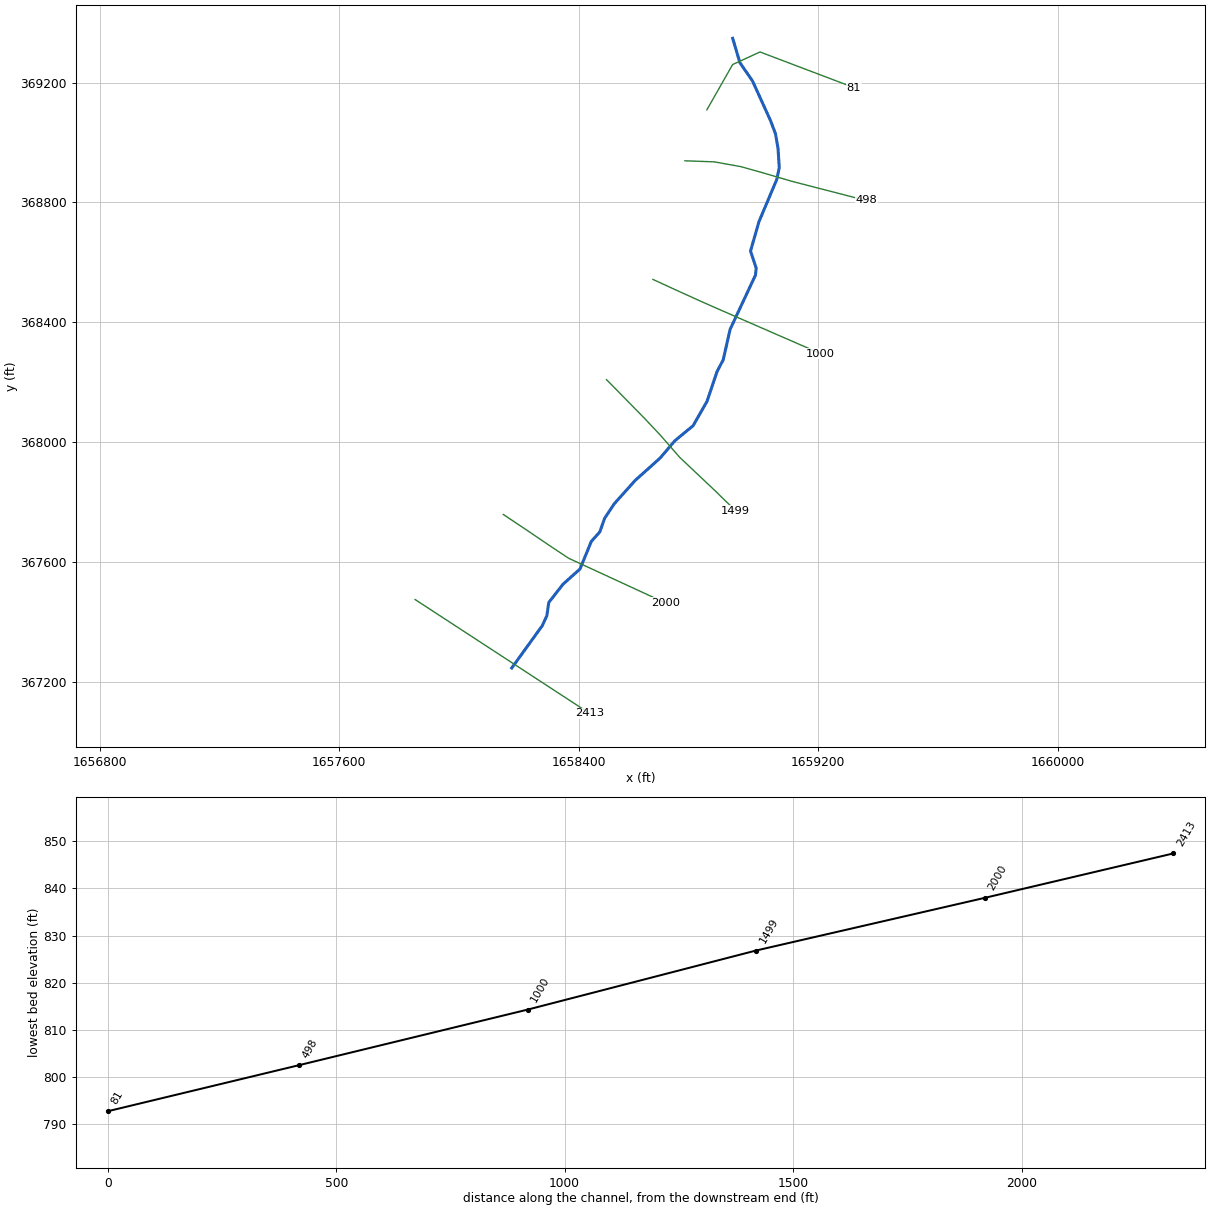
--- CRPNTRRN.prj (project) ---

Proj Title=CRPNTRRN
Current Plan=p01
Default Exp/Contr=0,0
English Units
Geom File=g01
Flow File=f01
Plan File=p01
BEGIN DESCRIPTION:
---------- MODELED AS PART OF WVEMD CTP PROGRAM, 2023----------
Stream Name: Carpenter Run
Flood Zone:  AFH
Wetzel County, WV
HEC-RAS Version: RAS 6.3
Vertical Datum: NAVD88
Projection: NAD 1983 StatePlane West Virginia S FIPS 4702 (US Feet)
Terrain: 1-meter West Virginia FEMA R3 South Central (collected 2018-2020)
Land Use: 2019 NLCD
Hydrologic Method:
WV 2010 Regional Regression Equations
Additional Model Notes:
None
END DESCRIPTION:
DSS Export Rating Curves= 0
DSS Export Rating Curve Sorted= 0
DSS Export Volume Flow Curves= 0
DXF OffsetX= 0
DXF OffsetY= 0
DXF ScaleX= 0
DXF ScaleY= 0

--- CRPNTRRN.p01 (plan) ---

Plan Title=Floodplain
Program Version=6.30
Short Identifier=Floodplain
Geom File=g01
Flow File=f01
Subcritical Flow
K Sum by GR= 0
Std Step Tol= 0.01
Critical Tol= 0.01
Num of Std Step Trials= 20
Max Error Tol= 0.3
Flow Tol Ratio= 0.001
Split Flow NTrial= 30
Split Flow Tol= 0.02
Split Flow Ratio= 0.02
Log Output Level= 0
Friction Slope Method= 1
Unsteady Friction Slope Method= 2
Unsteady Bridges Friction Slope Method= 1
Parabolic Critical Depth
Global Vel Dist= 0 , 0 , 0
Global Log Level= 0
CheckData=True
Encroach Param=-1 ,0,0, 0
Mapping Interval=1HOUR
Computation Time Step Use Courant=        0
Computation Time Step Use Time Series=    0
Computation Time Step Count To Double=0
Computation Time Step Max Doubling=0
Computation Time Step Max Halving=0
Computation Time Step Residence Courant=0
Run HTab= 0
Run UNet= 0
Run Sediment= 0
Run PostProcess= 0
Run WQNet= 0
Run RASMapper=-1
UNET Theta= 0
UNET Theta Warmup= 0
UNET ZTol= 0
UNET ZSATol= 0
UNET MxIter= 0
UNET Max Iter WO Improvement= 0
UNET MaxInSteps= 0
UNET DtIC= 0
UNET DtMin= 0
UNET MaxCRTS= 0
UNET WFStab= 0
UNET SFStab= 0
UNET WFX= 1
UNET SFX= 1
UNET Gravity=32.17405
UNET 1D Methodology=Finite Difference
UNET DSS MLevel= 1
UNET Pardiso=0
UNET DZMax Abort= 0
UNET Use Existing IB Tables= 0
UNET Froude Reduction=False
UNET Froude Limit= 0
UNET Froude Power= 0
UNET D1 Cores= 0
UNET WindReference=Eulerian
UNET WindDragFormulation=Hsu (1988)
UNET D2 Coriolis=0
UNET D2 Cores= 0
UNET D2 Theta= 1
UNET D2 Theta Warmup= 1
UNET D2 Z Tol= 0.01
UNET D2 Volume Tol= 0.01
UNET D2 Max Iterations= 20
UNET D2 Equation= 0
UNET D2 RampUpFraction=0.1
UNET D2 TimeSlices= 1
UNET D2 Turbulence Formulation=Non-Conservative (original)
UNET D2 Eddy Viscosity=0.3
UNET D2 Transverse Eddy Viscosity=0.1
UNET D2 Smagorinsky Mixing=0
UNET D2 BCVolumeCheck=0
UNET D2 Cores=0
UNET D2 SolverType=PARDISO (Direct)
UNET D2 Minimum Iterations= 3
UNET D2 Maximum Iterations= 30
UNET D2 Restart Number= 10
UNET D2 Relaxation Coeff=1.3
UNET D2 SOR Precondition Iterations= 10
UNET D2 ILUT Maximum Fill= 8
UNET D2 ILUT Tolerance=1E-08
UNET D2 Convergence Tolerance=0.00001
UNET D1D2 MaxIter= 0
UNET D1D2 ZTol=0.01
UNET D1D2 QTol=0.1
UNET D1D2 MinQTol=1
Write IC File= 0
Write IC File at Fixed DateTime=0
Write IC File at Sim End=0
Echo Input=False
Echo Parameters=False
Echo Output=False
Write Detailed= 0
HDF Write Warmup=0
HDF Write Time Slices=0
HDF Flush=0
HDF Compression= 1
HDF Chunk Size= 1
HDF Spatial Parts= 1
HDF Use Max Rows=0
HDF Fixed Rows= 1
Calibration Method= 0
Calibration Iterations= 20
Calibration Max Change=0.05
Calibration Tolerance=0.2
Calibration Maximum=1.5
Calibration Minimum=0.5
Calibration Optimization Method= 1
WQ AD Non Conservative
WQ ULTIMATE=-1
WQ Max Comp Step=1HOUR
WQ Output Interval=15MIN
WQ Output Selected Increments= 0
WQ Output face flow=0
WQ Output face velocity=0
WQ Output face area=0
WQ Output face dispersion=0
WQ Output cell volume=0
WQ Output cell surface area=0
WQ Output cell continuity=0
WQ Output cumulative cell continuity=0
WQ Output face conc=0
WQ Output face dconc_dx=0
WQ Output face courant=0
WQ Output face peclet=0
WQ Output face adv mass=0
WQ Output face disp mass=0
WQ Output cell mass=0
WQ Output cell source sink temp=0
WQ Output nsm pathways=0
WQ Output nsm derived pathways=0
WQ Create Restart=0
WQ Fixed Restart=0
WQ System Summary=0
WQ Write To DSS=0
Sorting and Armoring Iterations= 10
XS Update Threshold= 0.02
Bed Roughness Predictor= 0
Hydraulics Update Threshold= 0.02
Energy Slope Method= 1
Volume Change Method= 1
Sediment Retention Method= 0
Sediment TS Multiplier= 1
Warm Up Method= 0
XS Weighting Method= 0
Number of US Weighted Cross Sections= 1
Number of DS Weighted Cross Sections= 1
Upstream XS Weight=0
Main XS Weight=1
Downstream XS Weight=0
Number of DS XS's Weighted with US Boundary= 1
Upstream Boundary Weight= 1
Weight of XSs Associated with US Boundary= 0
Number of US XS's Weighted with DS Boundary= 1
Downstream Boundary Weight= 0.5
Weight of XSs Associated with DS Boundary= 0.5
Percentile Method= 0
Sediment Output Level= 3
Mass or Volume Output= 0
Output Increment Type= 1
Profile and TS Output Increment= 1
Transport Output Increment 1
XS Output Flag= 0
XS Output Increment= 10
Read HDF5 Sediment Hotstart= 0
Sediment Hotstart Type= 0
Write Gradation File= 0
Read Gradation Hotstart= 0
Write HDF5 File= 1
Write Binary Output= 1
Write DSS Sediment File= 0
DSS Sediment Output Type= 1
SV Curve= 0
Specific Gage Flag= 0
Subcell Erosion Methods= 0
Subcell Deposition Methods= 0
Advection Scheme= 1
Matrix Solver= 0
Implicit Weighting Factor= 1
Maximum Outer Loop Convergence Iterations= 5
Convergence Maximum Absolute= 0.001
Convergence RMSE= 0.0001
Grain Fractions Max Abs Error= 0.001
Max Subgrid Regions= 1
Max Subgrid Length Scale= 3.402823E+38
Initial Layer Thickness= 3.402823E+38
Min Layer Thickness= 3.402823E+38
Max Layer Thickness= 3.402823E+38
Number of Layers= 5

--- CRPNTRRN.f01 (steady flow) ---

Flow Title=Flow
Program Version=6.31
Number of Profiles= 1
Profile Names=F01pct
River Rch & RM=CRPNTRRN,Main            ,2413
     617
Boundary for River Rch & Prof#=CRPNTRRN,Main            , 1
Up Type= 0
Dn Type= 3
Dn Slope=0.02323
DSS Import GetInterval= 0
DSS Import GetPeak= 0
DSS Import FillOption= 0

--- CRPNTRRN.g01 (geometry) ---

Geom Title=Geometry
Program Version=6.30

River Reach=CRPNTRRN        ,Main
Reach XY= 30
     1658176.515      367245.416     1658278.382      367386.515
     1658293.868      367420.241     1658300.063      367463.947
     1658347.555      367524.861     1658404.339      367575.794
     1658442.194      367668.025     1658470.758       367700.03
     1658486.589      367745.113     1658518.938      367793.981
     1658589.144      367872.102     1658672.427      367946.781
     1658720.607      368003.565     1658782.209      368054.498
     1658828.324      368135.028     1658862.394      368235.862
     1658882.699      368274.406     1658905.756      368376.273
     1658990.416      368557.293     1658992.825      368580.695
     1658973.897      368637.822     1659002.117      368735.904
     1659061.654      368877.003     1659069.913      368916.579
     1659065.783      368980.246      1659057.18      369029.803
     1659040.661      369073.509      1658980.78      369205.316
      1658938.45      369266.9181658914.34756905369348.163453611

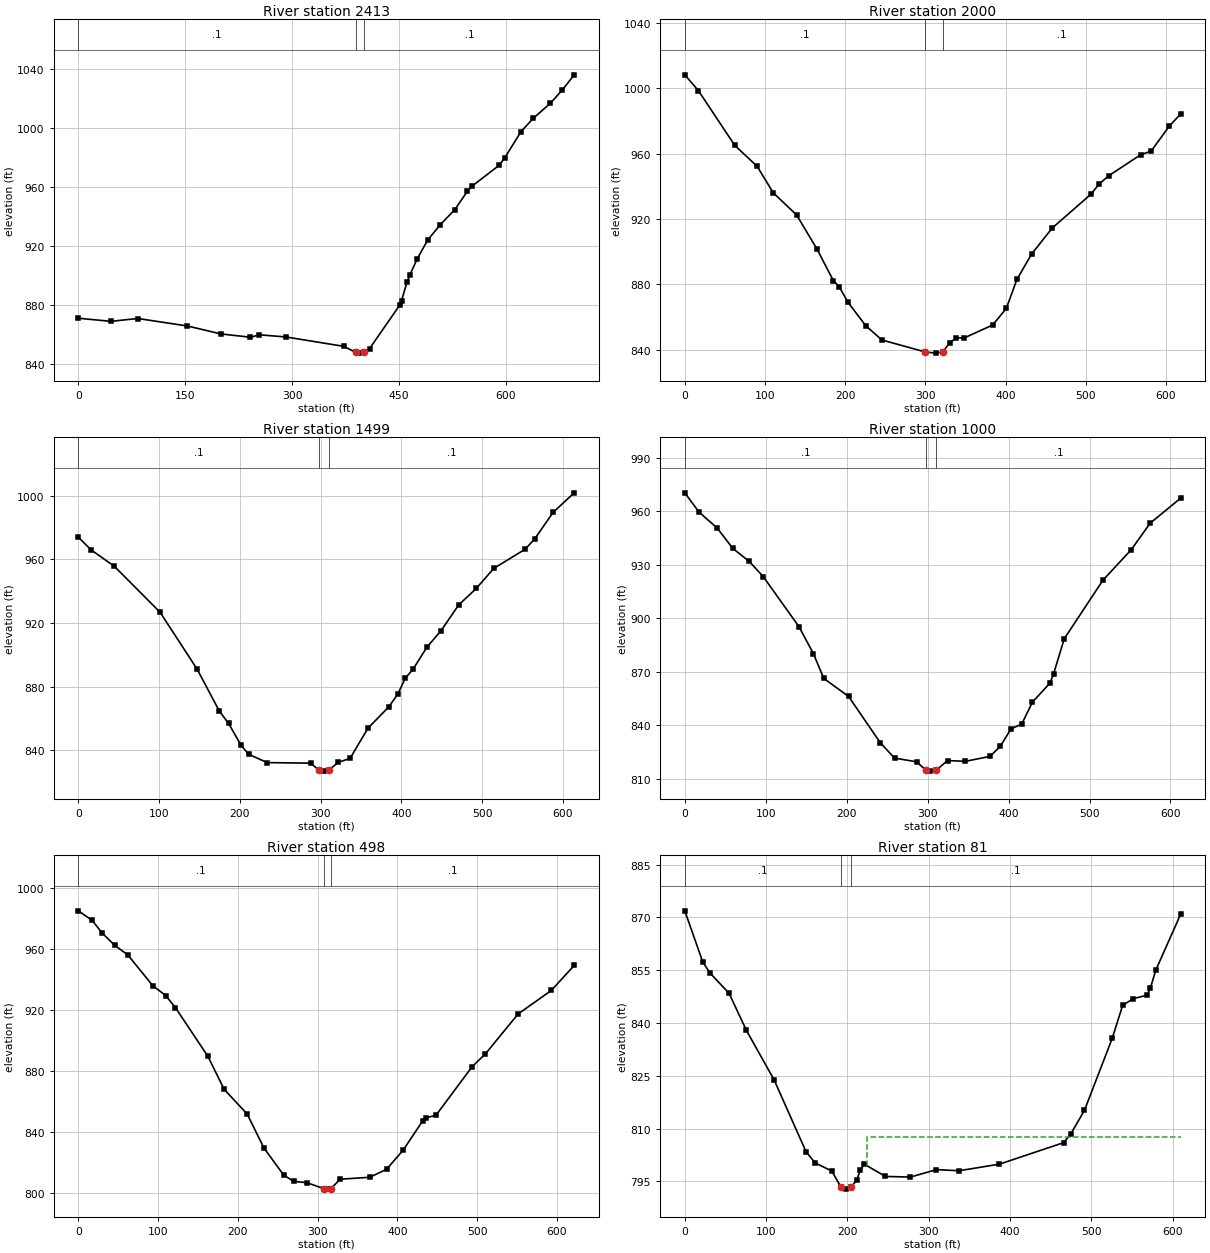
Type RM Length L Ch R = 1 ,2413    ,410.1,413.3,413.3
XS GIS Cut Line= 2
1657853.83725511367473.8217067131658436.38828242367093.671481763
#Sta/Elev= 30
       0  871.05    45.7  868.94    83.5  870.86   152.9  865.81     200  860.43
   241.5  858.18     254  859.83   291.6  858.34   372.5  852.02  389.13  847.94
   394.4  847.43   401.4  847.94   408.7  850.56   450.6   879.7   453.5     883
   461.2  895.63     465  900.25   475.6   911.4   489.9  923.78   507.4  934.15
   528.1   944.5   545.9  957.04   551.7  960.21   590.2  974.48     598  979.43
   621.1  997.39   638.4 1006.42   661.9 1016.39   678.9 1025.45695.6147 1035.78
#Mann= 3 ,-1,0
       0      .1       0  389.13    .045       0   401.4      .1       0
Bank Sta=389.13,401.4
XS Rating Curve= 0 ,0
Exp/Cntr(USF)=0,0
Exp/Cntr=0.3,0.1

Type RM Length L Ch R = 1 ,2000    ,504.4,500.7,497.4
XS GIS Cut Line= 6
1658148.37812492367757.9012653381658228.43111442367704.486674011
1658302.76790801367654.0123655051658365.97709918367611.992436424
 1658604.3165175 367501.989703671658689.43773834367462.703364924
#Sta/Elev= 30
       0 1008.11    16.9  998.47    62.2  965.04    90.2  952.17   110.4  935.94
   139.4  922.46   165.1  901.37   185.2  882.31   192.5  878.63   203.2  869.27
   225.6  854.76   245.8  846.02   299.6  838.75   312.8     838   321.6  838.76
   330.4  844.34   338.5  847.35   348.1  847.23   383.8  855.17   400.9  865.32
   414.1  883.04   432.5  898.61   458.2  914.49   506.6  935.21   516.4  941.29
   528.7  946.43   568.3  959.24   581.5   961.5   604.3  976.87618.2422  984.15
#Mann= 3 ,-1,0
       0      .1       0   299.6    .045       0   321.6      .1       0
Bank Sta=299.6,321.6
XS Rating Curve= 0 ,0
Exp/Cntr(USF)=0,0
Exp/Cntr=0.3,0.1

Type RM Length L Ch R = 1 ,1499    ,494.6,499.3,500.6
XS GIS Cut Line= 6
1658492.93452242368208.4023328421658620.06222093368078.845505342
1658671.54899459368024.1763233391658737.34545092 367948.85757634
1658855.86686742367836.9440862541658923.47007868367770.970793009
#Sta/Elev= 30
       0     974    15.9  965.98    44.4  955.78   101.2  926.81   147.2  890.91
   174.7  864.56     186  856.92   201.2  843.42   210.8  837.43   234.1  832.19
   287.9  831.85  297.77  827.48   303.9  826.83   310.3  827.48     322   832.4
   336.5  834.79   358.8  853.89   384.3  867.13   395.6  875.23   405.1  885.41
   414.5  890.89   431.8  904.84   449.3  915.21     471  931.35   492.8  941.73
   514.5  954.36   553.5  966.46   565.4  973.03     588  989.58614.1028 1001.91
#Mann= 3 ,-1,0
       0      .1       0  297.77    .045       0   310.3      .1       0
Bank Sta=297.77,310.3
XS Rating Curve= 0 ,0
Exp/Cntr(USF)=0,0
Exp/Cntr=0.3,0.1

Type RM Length L Ch R = 1 ,1000    ,499.6,501.7,502.1
XS GIS Cut Line= 6
1658647.94372684368542.9603907611658733.16763775368503.855810165
1658812.86957809368467.7243207541658881.52298409368437.528515011
1659041.94523542368367.6021456721659208.09614985 368295.17709367
#Sta/Elev= 30
       0  970.43    17.8   959.5    39.8  950.78    59.3  939.26    79.4  932.04
      97  923.39   140.9  895.43   158.9  880.24   171.7   866.3   202.3  856.24
   241.6  830.18   259.1  821.63   286.3  819.56  297.67  814.89   302.7  814.32
   310.7  814.89   324.6  820.25   346.4  819.81   376.9  822.56   389.7  828.18
   403.1   838.1   416.2  840.67   429.5  853.04   451.1  863.71   455.5  868.72
   468.7  888.53   516.5  921.39   551.5  938.52     575  953.45612.5269  967.42
#Mann= 3 ,-1,0
       0      .1       0  297.67    .045       0   310.7      .1       0
Bank Sta=297.67,310.7
XS Rating Curve= 0 ,0
Exp/Cntr(USF)=0,0
Exp/Cntr=0.3,0.1

Type RM Length L Ch R = 1 ,498     ,411.7,417.5,418.7
XS GIS Cut Line= 6
1658754.76044235368939.1892570851658853.13196476368935.615773425
1658942.00842743368919.579388171  1659015.671994368898.921949178
1659111.66720884368870.7084229291659359.78843176368806.678039178
#Sta/Elev= 30
       0  985.06    17.4  978.76    29.4  970.78    45.4  962.47    61.8  956.26
    93.4  935.95   109.6  929.45   121.8  921.49   162.4  889.64   182.8  867.96
   211.7  851.75   232.5  829.64   257.4  811.73   269.9  807.64   286.6  806.72
   307.4  802.88   312.6  802.51  316.64   802.9   328.3  809.01   365.3  810.29
   386.4  815.54   406.9  827.89   431.9  847.41     436  849.25   448.4     851
   493.8  882.93   510.4  891.29   551.3  917.41     593  932.86621.5586  949.21
#Mann= 3 ,-1,0
       0      .1       0   307.4    .045       0  316.64      .1       0
Bank Sta=307.4,316.64
XS Rating Curve= 0 ,0
Exp/Cntr(USF)=0,0
Exp/Cntr=0.3,0.1

Type RM Length L Ch R = 1 ,81      ,,,
XS GIS Cut Line= 4
1658827.99347016 369109.233164211658914.16950408369260.566687207
1659005.60017423369302.6037769291659318.77649265369183.848998466
#Sta/Elev= 30
       0  871.89    22.2  857.27    31.4  854.11    54.4  848.45    75.8  837.88
   109.7  823.89   149.2  803.36   160.3  800.22   180.7  797.92  192.17   793.3
   198.3  792.77  204.14  793.32   211.5  795.31   215.9  798.31   220.8  799.85
   246.7  796.38   277.5   796.2   309.4  798.31   337.3     798   386.9  799.87
   465.7  805.97   474.3  808.33   491.4  815.13   525.6  835.64   538.4     845
   551.4  846.92   568.4  847.91   572.6  849.99   579.2  855.03609.7172  870.91
#Mann= 3 ,-1,0
       0      .1       0  192.17    .045       0  204.14      .1       0
#XS Ineff= 2 , 0
                          223.57          807.57
Permanent Ineff=
       F       F
Bank Sta=192.17,204.14
XS Rating Curve= 0 ,0
Exp/Cntr(USF)=0,0
Exp/Cntr=0.3,0.1
LCMann Table=0

Chan Stop Cuts=-1
Use User Specified Reach Order=0
Composite Channel Slope=5